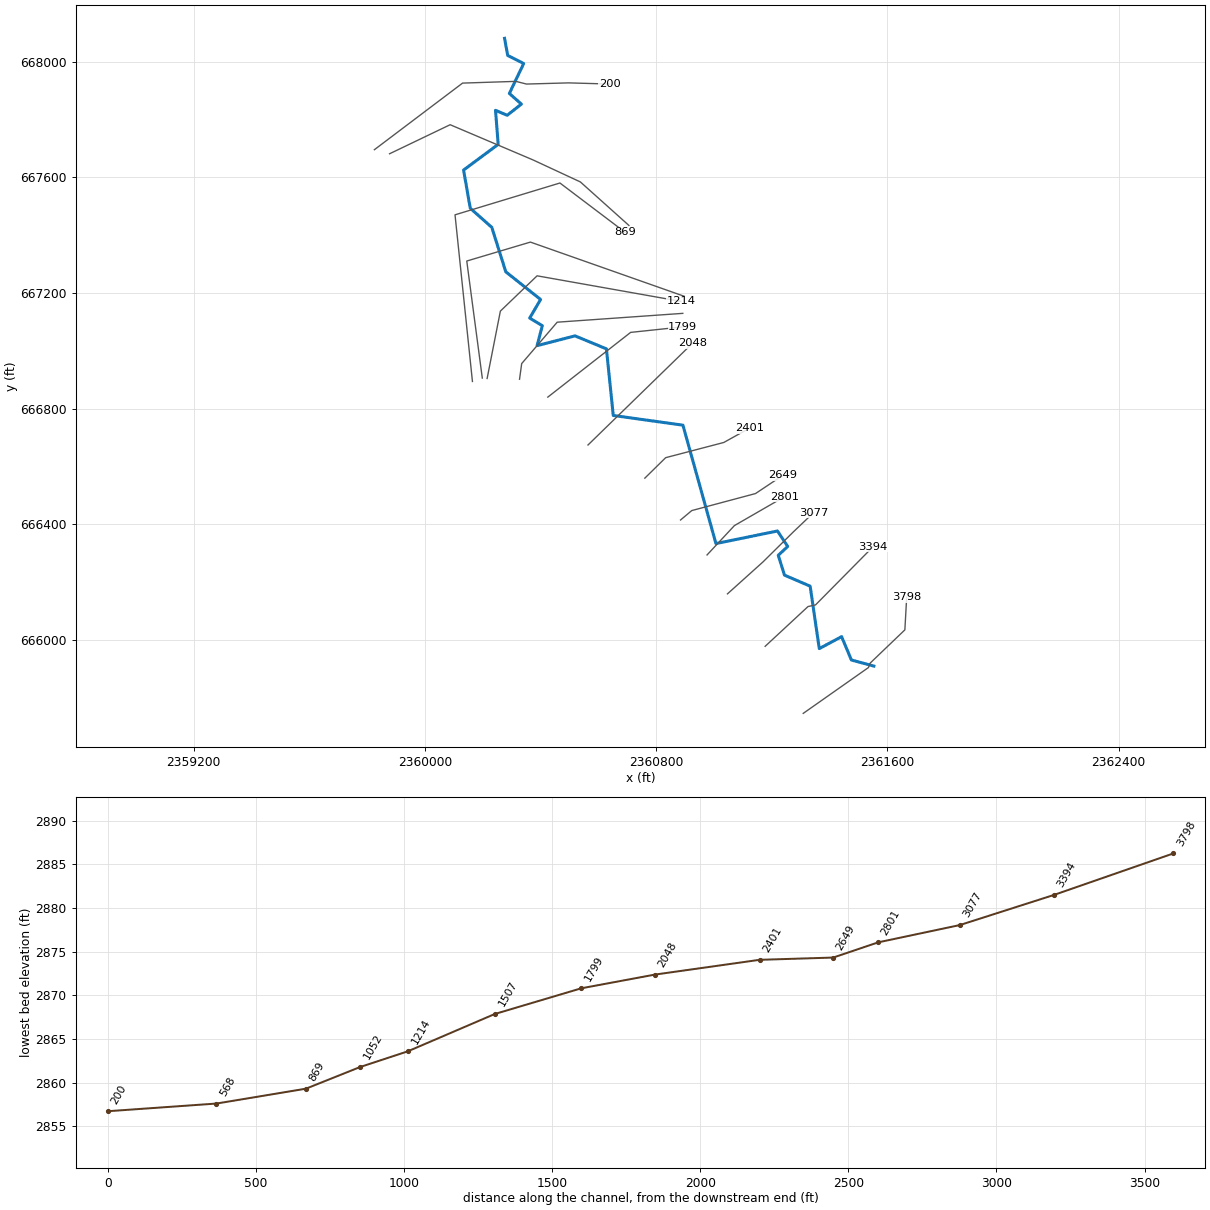
--- BNNETTRN.prj (project) ---

Proj Title=BNNETTRN
Current Plan=p01
Default Exp/Contr=0,0
English Units
Geom File=g01
Flow File=f01
Plan File=p01
Background Map Layer=Inundation Boundary (P100yr Value_0)
BEGIN DESCRIPTION:
----------MODEL BY WOOD PLC 2022----------
AFH study
Randolph County, WV
HEC-RAS Version: RAS 6.2
Vertical Datum: NAVD88
Projection: NAD 1983 StatePlane West Virginia S FIPS 4702 (US Feet)
Terrain: 1-meter LIDAR (FEMA Region III 3DEP collected 2016-2018)
Land Use: 2019 NLCD
Hydrologic Method:
WV SIR2010-5033 regression equations
Additional Model Notes:
None
END DESCRIPTION:
DSS File=dss
DSS Export Rating Curves= 0
DSS Export Rating Curve Sorted= 0
DSS Export Volume Flow Curves= 0
DXF OffsetX= 0
DXF OffsetY= 0
DXF ScaleX= 0
DXF ScaleY= 0

--- BNNETTRN.p01 (plan) ---

Plan Title=Floodplain
Program Version=6.20
Short Identifier=Floodplain
Geom File=g01
Flow File=f01
Subcritical Flow
K Sum by GR= 0
Std Step Tol= 0.01
Critical Tol= 0.01
Num of Std Step Trials= 20
Max Error Tol= 0.3
Flow Tol Ratio= 0.001
Split Flow NTrial= 30
Split Flow Tol= 0.02
Split Flow Ratio= 0.02
Log Output Level= 0
Friction Slope Method= 1
Unsteady Friction Slope Method= 2
Unsteady Bridges Friction Slope Method= 1
Parabolic Critical Depth
Global Vel Dist= 0 , 0 , 0
Global Log Level= 0
CheckData=True
Encroach Param=-1 ,0,0, 0
Computation Interval=0.1SEC
Output Interval=1SEC
Instantaneous Interval=Max Profile
Mapping Interval=1HOUR
Computation Time Step Use Courant=        0
Computation Time Step Use Time Series=    0
Computation Time Step Count To Double=0
Computation Time Step Max Doubling=0
Computation Time Step Max Halving=0
Computation Time Step Residence Courant=0
Run HTab= 0
Run UNet= 0
Run Sediment= 0
Run PostProcess= 0
Run WQNet= 0
Run RASMapper=-1
UNET Theta= 0
UNET Theta Warmup= 0
UNET ZTol= 0
UNET ZSATol= 0
UNET MxIter= 0
UNET Max Iter WO Improvement= 0
UNET MaxInSteps= 0
UNET DtIC= 0
UNET DtMin= 0
UNET MaxCRTS= 0
UNET WFStab= 0
UNET SFStab= 0
UNET WFX= 1
UNET SFX= 1
UNET Gravity=32.174
UNET 1D Methodology=Finite Difference
UNET DSS MLevel= 1
UNET Pardiso=0
UNET DZMax Abort= 0
UNET Use Existing IB Tables= 0
UNET Froude Reduction=False
UNET Froude Limit= 0
UNET Froude Power= 0
UNET D1 Cores= 0
UNET WindReference=Eulerian
UNET WindDragFormulation=Hsu (1988)
UNET D2 Coriolis=0
UNET D2 Cores= 0
UNET D2 Theta= 1
UNET D2 Theta Warmup= 1
UNET D2 Z Tol= 0.01
UNET D2 Volume Tol= 0.01
UNET D2 Max Iterations= 20
UNET D2 Equation= 0
UNET D2 RampUpFraction=0.1
UNET D2 TimeSlices= 1
UNET D2 Turbulence Formulation=Non-Conservative (original)
UNET D2 Eddy Viscosity=0.3
UNET D2 Transverse Eddy Viscosity=0.1
UNET D2 Smagorinsky Mixing=0
UNET D2 BCVolumeCheck=0
UNET D2 Cores=0
UNET D2 SolverType=PARDISO (Direct)
UNET D2 Minimum Iterations= 2147483647
UNET D2 Maximum Iterations= 2147483647
UNET D2 Restart Number= 10
UNET D2 Relaxation Coeff=1.3
UNET D2 SOR Precondition Iterations= 10
UNET D2 ILUT Maximum Fill= 8
UNET D2 ILUT Tolerance=1E-08
UNET D1D2 MaxIter= 0
UNET D1D2 ZTol=0.01
UNET D1D2 QTol=0.1
UNET D1D2 MinQTol=1
DSS File=dss
Write IC File= 0
Write IC File at Fixed DateTime=0
Write IC File at Sim End=0
Echo Input=False
Echo Parameters=False
Echo Output=False
Write Detailed= 0
HDF Write Warmup=0
HDF Write Time Slices=0
HDF Flush=0
HDF Compression= 1
HDF Chunk Size= 1
HDF Spatial Parts= 1
HDF Use Max Rows=0
HDF Fixed Rows= 1
Calibration Method= 0
Calibration Iterations= 20
Calibration Max Change=0.05
Calibration Tolerance=0.2
Calibration Maximum=1.5
Calibration Minimum=0.5
Calibration Optimization Method= 1
WQ AD Non Conservative
WQ ULTIMATE=-1
WQ Max Comp Step=1HOUR
WQ Output Interval=15MIN
WQ Output Selected Increments= 0
WQ Output face flow=0
WQ Output face velocity=0
WQ Output face area=0
WQ Output face dispersion=0
WQ Output cell volume=0
WQ Output cell surface area=0
WQ Output cell continuity=0
WQ Output cumulative cell continuity=0
WQ Output face conc=0
WQ Output face dconc_dx=0
WQ Output face courant=0
WQ Output face peclet=0
WQ Output face adv mass=0
WQ Output face disp mass=0
WQ Output cell mass=0
WQ Output cell source sink temp=0
WQ Output nsm pathways=0
WQ Output nsm derived pathways=0
WQ Create Restart=0
WQ Fixed Restart=0
WQ System Summary=0
WQ Write To DSS=0
Sorting and Armoring Iterations= 10
XS Update Threshold= 0.02
Bed Roughness Predictor= 0
Hydraulics Update Threshold= 0.02
Energy Slope Method= 1
Volume Change Method= 1
Sediment Retention Method= 0
Sediment TS Multiplier= 1
Warm Up Method= 0
XS Weighting Method= 0
Number of US Weighted Cross Sections= 1
Number of DS Weighted Cross Sections= 1
Upstream XS Weight=0
Main XS Weight=1
Downstream XS Weight=0
Number of DS XS's Weighted with US Boundary= 1
Upstream Boundary Weight= 1
Weight of XSs Associated with US Boundary= 0
Number of US XS's Weighted with DS Boundary= 1
Downstream Boundary Weight= 0.5
Weight of XSs Associated with DS Boundary= 0.5
Percentile Method= 0
Sediment Output Level= 3
Mass or Volume Output= 0
Output Increment Type= 1
Profile and TS Output Increment= 1
Transport Output Increment 1
XS Output Flag= 0
XS Output Increment= 10
Read HDF5 Sediment Hotstart= 0
Sediment Hotstart Type= 0
Write Gradation File= 0
Read Gradation Hotstart= 0
Write HDF5 File= 1
Write Binary Output= 1
Write DSS Sediment File= 0
DSS Sediment Output Type= 1
SV Curve= 0
Specific Gage Flag= 0
Subcell Erosion Methods= 0
Subcell Deposition Methods= 0
Advection Scheme= 1
Matrix Solver= 0
Implicit Weighting Factor= 1
Maximum Outer Loop Convergence Iterations= 5
Convergence Maximum Absolute= 0.001
Convergence RMSE= 0.0001
Grain Fractions Max Abs Error= 0.001
Max Subgrid Regions= 1
Max Subgrid Length Scale= 3.402823E+38
Initial Layer Thickness= 3.402823E+38
Min Layer Thickness= 3.402823E+38
Max Layer Thickness= 3.402823E+38
Number of Layers= 5

--- BNNETTRN.f01 (steady flow) ---

Flow Title=Flow
Program Version=4.00
Number of Profiles=1
Profile Names=P100yr
River Rch & RM=BNNETTRN,Main,3798
     373
Boundary for River Rch & Prof#=BNNETTRN,Main      ,1
Up Type=0
Dn Type=3
Dn Slope=0.008388

--- BNNETTRN.g01 (geometry) ---

Geom Title=Geometry
Program Version=6.20

River Reach=BNNETTRN        ,Main
Reach XY= 30
2361553.43439557665909.4790226942361475.68468542665930.483688451
2361441.78333894666011.3029665682361364.55306684 665969.96310029
2361332.95494989666185.9029164392361244.27100001666224.018999994
2361222.63099998666292.7090000212361255.27065319666323.262944631
2361219.96200003666376.7700000112361007.08500002666333.268000022
2360892.86999999666742.8129999942360651.88400005666776.432999998
2360628.24567494667006.8423815022360519.53900003667051.744000018
2360388.40799999667017.9260000142360406.54493319667086.910322195
2360362.75300001667113.3440000122360400.51820523667177.461949875
2360280.07500002667273.5250000062360231.72900002667427.165000007
2360157.22300005 667493.201000022360134.07900003667625.300000012
     2360253.794667714.121000007     2360244.579667831.986000016
2360285.06700003667814.7690000092360334.06717459667853.624390923
2360292.43626311 667890.259593022360342.06030959667993.837300767
2360286.77445915668021.8132732772360275.82015684668080.982344916

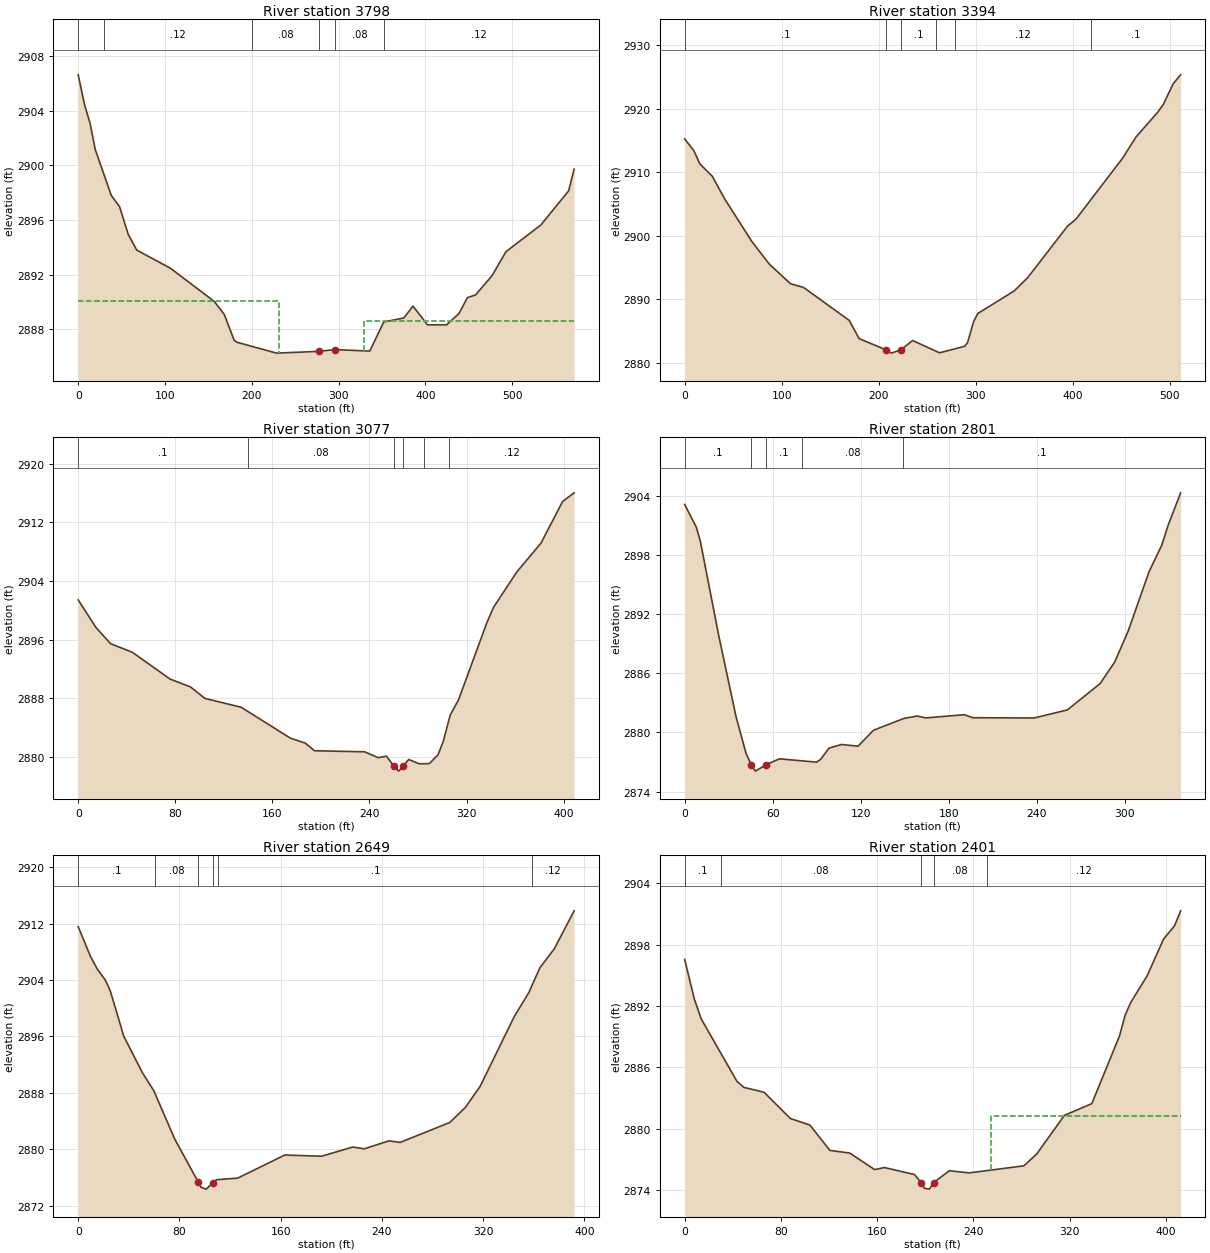
Type RM Length L Ch R = 1 ,3798    ,405.6,403.9,387.2
XS GIS Cut Line= 5
 2361309.0647921665745.8827289542361534.67219736665904.434599875
2361540.93906973665920.1017807962361660.63633197666034.785545138
2361666.90320434666147.589247769
#Sta/Elev= 30
       0 2906.61     7.5 2904.37    13.6 2903.09    19.6 2901.15      38  2897.8
    47.7 2896.96    57.6 2894.94    67.4 2893.79   106.5 2892.45   156.8 2890.03
   168.3 2889.08   179.6  2887.2   182.6 2887.05   228.6 2886.25   277.5 2886.38
   295.7 2886.51   335.9  2886.4     352 2888.53   375.1 2888.82   385.7 2889.69
   402.4 2888.32   424.5 2888.32   438.7 2889.15   448.4 2890.31   457.8 2890.51
   476.8 2891.92   492.8 2893.67   532.9 2895.62     565 2898.12571.3708 2899.71
#Mann= 6 ,-1,0
       0      .1       0      30     .12       0     200     .08       0
   277.5    .045       0   295.7     .08       0  352.62     .12       0
#XS Ineff= 2 , 0
           230.9 2890.03  329.68         2888.59
Permanent Ineff=
       F       F
Bank Sta=277.5,295.7
XS Rating Curve= 0 ,0
Exp/Cntr(USF)=0,0
Exp/Cntr=0.3,0.1

Type RM Length L Ch R = 1 ,3394    ,309.2,317,315.6
XS GIS Cut Line= 4
2361177.30669706 665977.812298212361325.64356602666115.432815421
2361351.58841762666121.0730005532361550.12293425666321.863591237
#Sta/Elev= 30
       0 2915.25     9.4 2913.41    15.7 2911.31    28.5 2909.36    41.2  2905.8
    69.5 2899.03    87.3 2895.51   109.1 2892.43   122.6 2891.84   169.6 2886.65
   179.9 2883.77  207.42 2882.02   213.1 2881.49   222.8 2882.02     235 2883.47
   262.8 2881.54   288.8 2882.58   291.6 2883.15     298 2886.52   302.2 2887.74
   339.7 2891.29   353.8 2893.42   394.7 2901.51   403.4 2902.61   451.6 2912.24
   465.3 2915.56   487.8 2919.48   493.4 2920.69   503.7 2923.97511.2652 2925.35
#Mann= 6 ,-1,0
       0      .1       0  207.42    .045       0   222.8      .1       0
   258.9     .08       0   278.9     .12       0   418.9      .1       0
Bank Sta=207.42,222.8
XS Rating Curve= 0 ,0
Exp/Cntr(USF)=0,0
Exp/Cntr=0.3,0.1

Type RM Length L Ch R = 1 ,3077    ,275.2,275.6,273.2
XS GIS Cut Line= 4
2361047.02402234 666159.358892842361169.98005822666269.906521425
2361274.88750167666373.6859278522361344.26177879666439.676093895
#Sta/Elev= 30
       0 2901.43    14.7 2897.65    26.7 2895.45    44.6 2894.28    75.7 2890.62
    92.5 2889.55   104.4 2887.98   134.3 2886.77   174.9 2882.55   187.1 2881.88
   194.7 2880.83     236 2880.69   247.2 2879.89   254.1 2880.09  260.03 2878.75
   264.1 2878.05  267.89 2878.76   272.4 2879.64     281 2879.05   289.4 2879.08
   296.5 2880.28   300.8 2882.08   306.5 2885.68   313.5 2887.82   336.8 2898.33
   342.3 2900.43   361.6 2905.28   381.4 2909.19   399.2 2914.87   408.7 2916.05
#Mann= 6 ,-1,0
       0      .1       0     140     .08       0  260.03    .045       0
  267.89     .08       0  285.34      .1       0  305.34     .12       0
Bank Sta=260.03,267.89
XS Rating Curve= 0 ,0
Exp/Cntr(USF)=0,0
Exp/Cntr=0.3,0.1

Type RM Length L Ch R = 1 ,2801    ,153.4,151.9,147.5
XS GIS Cut Line= 3
2360976.32605111666293.9289304152361070.88791127666395.368016768
2361243.67821938666495.087796573
#Sta/Elev= 30
       0 2903.12     7.9 2900.83    10.7 2899.38    23.2 2889.84      35 2881.61
    41.8  2877.9   45.39 2876.72    48.2 2876.07    55.72876.733    64.6 2877.32
    89.9 2876.98    92.8 2877.27    98.4  2878.4   106.9 2878.77   118.2  2878.6
   128.8 2880.22   149.4 2881.41   158.5 2881.66   164.4 2881.47   190.7 2881.79
   196.6 2881.49   238.3 2881.46     261 2882.28   283.3 2884.95   293.2 2887.12
   302.4 2890.26   316.6 2896.27   325.4 2899.01   329.5 2900.93   338.2  2904.3
#Mann= 5 ,-1,0
       0      .1       0   45.39    .045       0    55.7      .1       0
      80     .08       0  148.68      .1       0
Bank Sta=45.39,55.7
XS Rating Curve= 0 ,0
Exp/Cntr(USF)=0,0
Exp/Cntr=0.3,0.1

Type RM Length L Ch R = 1 ,2649    ,245.3,248.6,244.5
XS GIS Cut Line= 4
2360884.57341707666414.8061187012360923.42802575666447.393855018
2361144.02193313666506.3024552852361238.02501867666568.971178972
#Sta/Elev= 30
       0 2911.57     9.9 2907.28    15.1 2905.56    21.3 2904.04    24.1 2902.99
    25.6 2902.32      36 2896.04    50.7 2890.87    59.8 2888.28    76.3 2881.43
      952875.299      97 2874.61   101.2 2874.33  106.35 2875.26   109.4 2875.67
     126 2875.89   163.3 2879.17   192.3    2879   217.1 2880.31     226 2880.05
   245.6 2881.18   254.4 2880.96   293.6 2883.78   305.9  2885.9   317.7 2888.92
   344.7 2898.84   356.2 2902.23   364.9 2905.74   376.4 2908.47     392 2913.83
#Mann= 6 ,-1,0
       0      .1       0   60.71     .08       0      95    .045       0
  106.35     .08       0  110.71      .1       0  359.04     .12       0
Bank Sta=95,106.35
XS Rating Curve= 0 ,0
Exp/Cntr(USF)=0,0
Exp/Cntr=0.3,0.1

Type RM Length L Ch R = 1 ,2401    ,348.6,353.2,350.2
XS GIS Cut Line= 4
 2360761.1160314666559.5708704192360833.18506364666630.386528186
2361034.35166668666683.0282560842361124.59462879666733.163235034
#Sta/Elev= 30
       0 2896.55       8 2892.69    13.7 2890.74    43.5 2884.61    49.2 2884.03
      66 2883.55    87.9 2880.98   104.1 2880.34   120.7 2877.86   137.2  2877.6
   157.9 2875.98   166.1 2876.18     191  2875.5   196.7 2874.69   199.2 2874.16
   203.4 2874.07   206.9  2874.7   219.9 2875.87   236.4 2875.66   281.9 2876.35
   292.6 2877.51   315.6 2881.29   338.4 2882.44   361.4 2889.06     366 2891.07
   370.7 2892.33   384.3 2894.93     398 2898.54   407.2 2899.85   412.2 2901.31
#Mann= 5 ,-1,0
       0      .1       0      30     .08       0   196.7    .045       0
   206.9     .08       0  251.04     .12       0
#XS Ineff= 2 , 0
                          255.01          2881.2
Permanent Ineff=
       F       F
Bank Sta=196.7,206.9
XS Rating Curve= 0 ,0
Exp/Cntr(USF)=0,0
Exp/Cntr=0.3,0.1

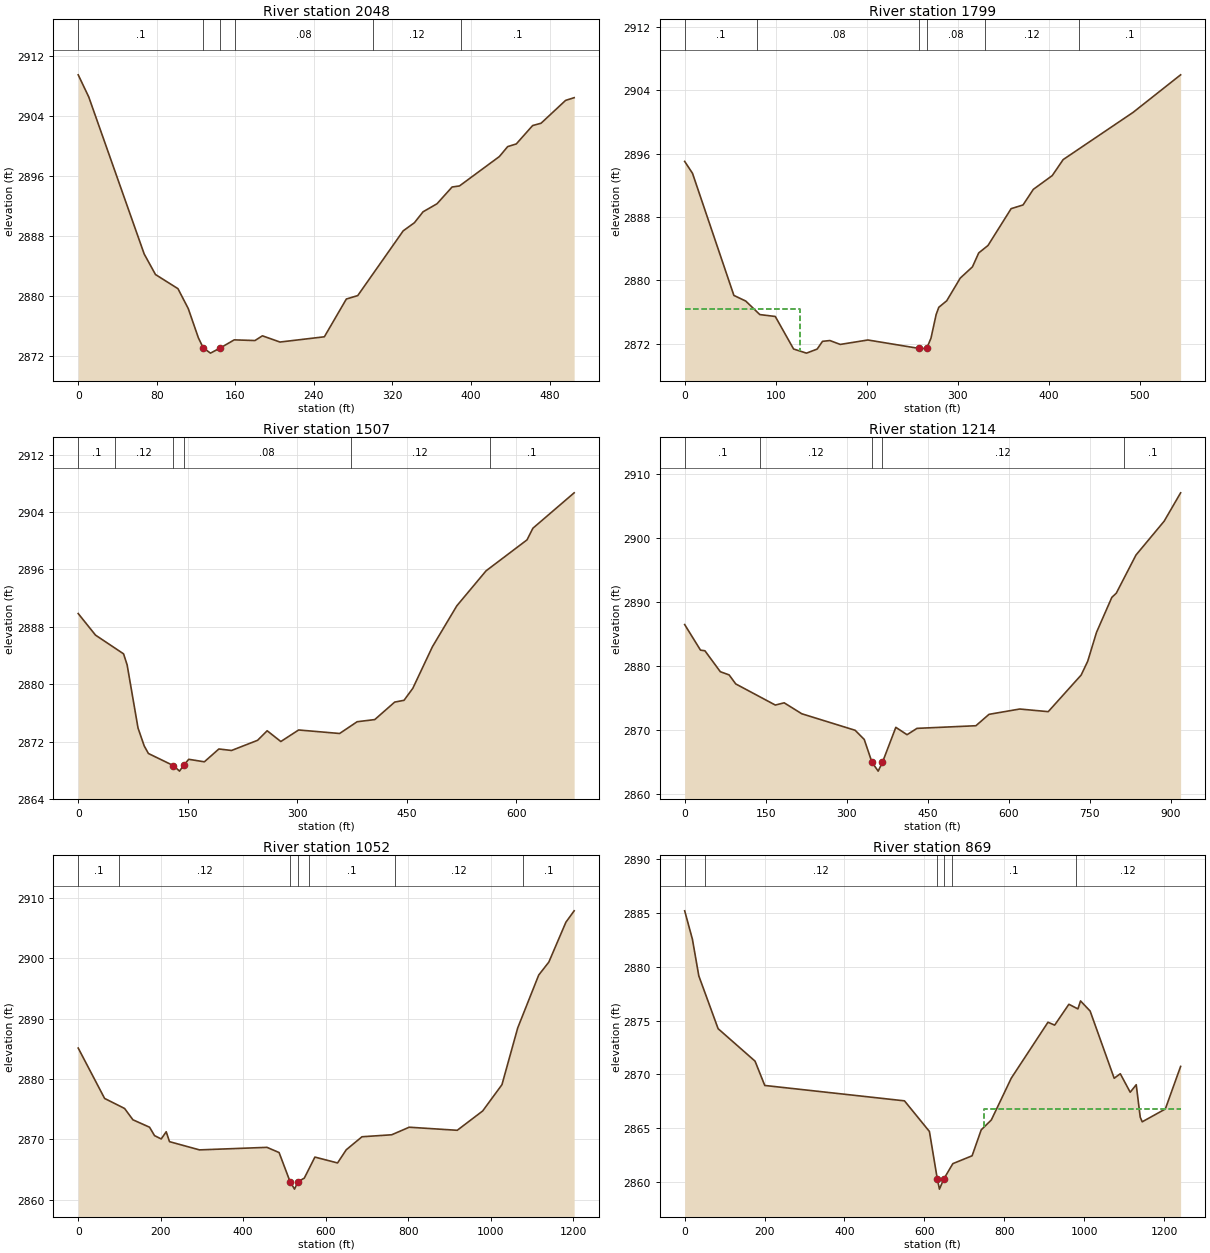
Type RM Length L Ch R = 1 ,2048    ,250,248.7,242.9
XS GIS Cut Line= 2
2360564.50801309666674.3049145832360926.41142849667026.656626943
#Sta/Elev= 30
       0 2909.52    10.7 2906.58    67.2 2885.61    78.7 2882.87   101.6 2880.98
   112.1 2878.32   122.4 2874.42  127.31 2873.09   134.7 2872.38   144.7 2873.07
   158.9 2874.15     180 2874.06   187.6 2874.69   205.5 2873.86   250.7 2874.56
   273.1  2879.6   284.7 2880.06     331  2888.7   342.4 2889.78   351.2 2891.24
   365.4 2892.31   380.8 2894.55   388.3 2894.69   428.9 2898.61   437.4 2899.94
   446.2  2900.3   462.8 2902.75   471.4 2903.06   496.4 2906.11505.0998 2906.47
#Mann= 6 ,-1,0
       0      .1       0  127.31    .045       0   144.7      .1       0
     160     .08       0     300     .12       0     390      .1       0
Bank Sta=127.31,144.7
XS Rating Curve= 0 ,0
Exp/Cntr(USF)=0,0
Exp/Cntr=0.3,0.1

Type RM Length L Ch R = 1 ,1799    ,289.1,291.8,286.8
XS GIS Cut Line= 3
2360425.47766875666839.8677673792360712.02876013667063.802138789
2360892.44981766 667082.90554488
#Sta/Elev= 30
       0 2895.03     8.6 2893.53    54.1  2878.1    67.1 2877.39    82.6 2875.68
    99.6 2875.44   119.7 2871.33   133.9 2870.81   145.6 2871.32   151.5  2872.3
   159.6  2872.4     171 2871.91   201.4 2872.47   257.3 2871.41  265.97  2871.4
   270.7 2872.69   276.4 2875.69   279.3  2876.6     288 2877.42   302.9 2880.29
   316.3 2881.71   323.2 2883.47   333.4 2884.41   358.8 2889.06   371.9 2889.53
   383.2  2891.5     404 2893.24     416 2895.26   492.8 2901.22545.1027 2905.97
#Mann= 6 ,-1,0
       0      .1       0      80     .08       0   257.3    .045       0
  265.97     .08       0     330     .12       0  433.67      .1       0
#XS Ineff= 2 , 0
          126.78  2876.4
Permanent Ineff=
       F       F
Bank Sta=257.3,265.97
XS Rating Curve= 0 ,0
Exp/Cntr(USF)=0,0
Exp/Cntr=0.3,0.1

Type RM Length L Ch R = 1 ,1507    ,281.3,293.5,285.7
XS GIS Cut Line= 4
2360327.68733512666901.6670784162360335.11643748666955.904160071
2360457.96079419667099.0763526832360892.44981766667129.602759772
#Sta/Elev= 30
       0 2889.85    23.7 2886.84    62.1 2884.23      67 2882.68    81.9 2873.88
    90.4 2871.38    96.1 2870.33   130.32868.641   138.7 2867.87   144.3 2868.67
   151.3 2869.52   172.7 2869.17   192.6 2870.96   209.9 2870.75   245.6 2872.17
   258.7  2873.5   277.4    2872   301.8 2873.61   357.9 2873.12   381.9 2874.76
     406 2875.06   433.3  2877.5   446.1 2877.75   458.1 2879.42     485 2885.23
   518.3 2890.92   558.4 2895.81   614.5 2900.13   622.5 2901.75     679 2906.69
#Mann= 6 ,-1,0
       0      .1       0      50     .12       0   130.3    .045       0
   144.3     .08       0  373.39     .12       0  563.39      .1       0
Bank Sta=130.3,144.3
XS Rating Curve= 0 ,0
Exp/Cntr(USF)=0,0
Exp/Cntr=0.3,0.1

Type RM Length L Ch R = 1 ,1214    ,164.3,162,155.5
XS GIS Cut Line= 4
2360215.58914873666904.3843459772360261.39097279667137.401304722
2360388.39047358667259.4788479232360885.52833581667171.177710213
#Sta/Elev= 30
       0 2886.49    29.3  2882.5    37.5  2882.4      66 2879.13    82.3 2878.63
    94.6 2877.22   167.9 2873.92   184.3 2874.27   216.9 2872.56   315.7 2869.98
   332.6 2868.55   346.8 2865.01   346.8    2865   358.4  2863.6  366.21 2864.95
   391.1 2870.44   411.9 2869.29   430.3 2870.28   539.4 2870.69   563.7 2872.47
   620.6  2873.3   673.4 2872.89   734.4 2878.61   746.5 2880.76   762.8 2885.27
   791.2 2890.74   799.4 2891.39   835.9 2897.35   888.1 2902.64   918.6 2907.07
#Mann= 5 ,-1,0
       0      .1       0     140     .12       0   346.8    .045       0
  366.21     .12       0  813.63      .1       0
Bank Sta=346.8,366.21
XS Rating Curve= 0 ,0
Exp/Cntr(USF)=0,0
Exp/Cntr=0.3,0.1

Type RM Length L Ch R = 1 ,1052    ,181.9,182.2,182.3
XS GIS Cut Line= 4
2360198.84927655 666905.762512222360145.12913597667310.628937623
2360365.25068764667376.1413041932360897.21110419667188.775935803
#Sta/Elev= 30
       0 2885.12      64 2876.79   112.4 2875.13   132.6 2873.26   172.9 2872.03
     185 2870.64   201.2 2870.09   213.3 2871.28   221.3 2869.64     294 2868.28
   457.5  2868.7   486.9 2867.84  513.63 2863.01   524.3 2861.79   532.6 2863.01
     548 2863.61   573.7 2867.09   628.6 2866.12   649.7  2868.3   687.8 2870.45
   759.9 2870.78   802.3 2872.03   918.7 2871.52   980.4 2874.72  1027.1 2879.07
  1065.3 2888.46  1116.2  2897.2  1140.7 2899.34  1182.1 2905.941202.071 2907.82
#Mann= 7 ,-1,0
       0      .1       0     100     .12       0  513.63    .045       0
   532.6     .12       0  558.41      .1       0  768.08     .12       0
 1078.08      .1       0
Bank Sta=513.63,532.6
XS Rating Curve= 0 ,0
Exp/Cntr(USF)=0,0
Exp/Cntr=0.3,0.1

Type RM Length L Ch R = 1 ,869     ,304.5,301.8,293.2
XS GIS Cut Line= 4
2360164.78284594666893.9702862372360104.51146869667470.479112054
2360467.44997949667580.5398878922360692.82562969667410.039337689
#Sta/Elev= 30
       0  2885.2    19.3 2882.57    35.4 2879.15    83.7 2874.24   176.2 2871.22
   200.5 2868.96   550.2 2867.53   612.7 2864.68   632.5 2860.24   637.8 2859.32
   648.9 2860.28   671.3 2861.69   719.5 2862.42   742.3 2864.83   767.6 2865.75
   817.6 2869.64   909.5 2874.84   926.2 2874.57   961.8 2876.51   984.4 2876.08
     991 2876.82    1015 2875.88  1075.2 2869.63  1090.5 2870.05  1115.3 2868.33
  1130.4 2869.03  1140.4 2866.01  1145.4 2865.58  1203.2 2866.77  1241.5 2870.73
#Mann= 6 ,-1,0
       0      .1       0      50     .12       0   632.5    .045       0
   648.9     .12       0  669.65      .1       0  978.91     .12       0
#XS Ineff= 2 , 0
                          749.03         2866.78
Permanent Ineff=
       F       F
Bank Sta=632.5,648.9
XS Rating Curve= 0 ,0
Exp/Cntr(USF)=0,0
Exp/Cntr=0.3,0.1

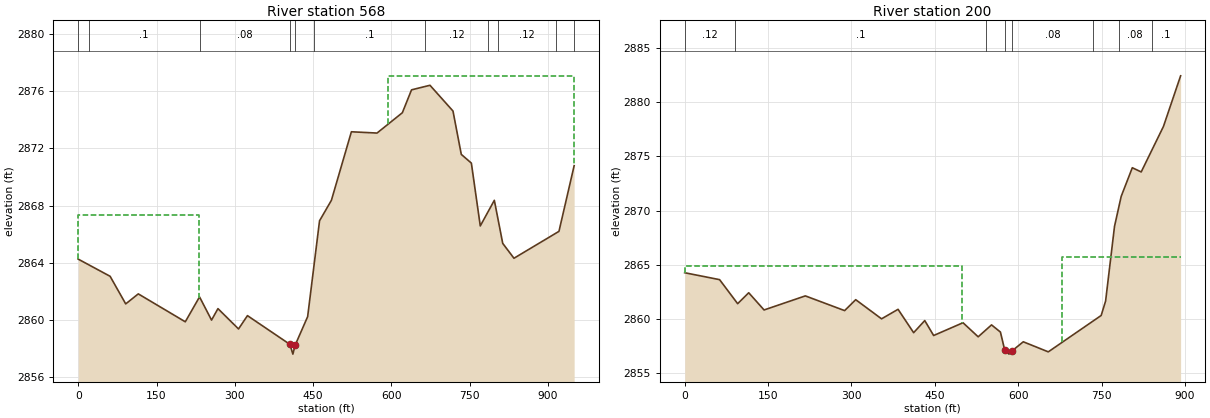
Type RM Length L Ch R = 1 ,568     ,357.7,367.4,360.2
XS GIS Cut Line= 5
2359878.10718093667681.6690137752360087.63792657667782.168685159
 2360374.6494613667660.2356826512360538.17125831667584.207709995
2360706.00338061667433.755054801
#Sta/Elev= 30
       0 2864.26    61.1 2863.06      91 2861.13   115.1 2861.83   205.1 2859.88
   232.4 2861.62   255.4    2860   267.7  2860.8   307.1 2859.38   324.2 2860.31
   405.52858.302   411.2 2857.62   415.5 2858.24   439.5 2860.24   462.3 2866.94
     485 2868.37   523.3 2873.16   572.4 2873.07   620.9 2874.49   638.5 2876.09
   673.8 2876.41   717.9 2874.61   733.8 2871.58   753.1 2870.97   770.2 2866.58
   797.1 2868.37   813.2 2865.36   834.7 2864.32   920.9  2866.2     950 2870.79
#Mann= 11 ,-1,0
       0     .12       0      20      .1       0  232.39     .08       0
   405.5    .045       0   415.5     .08       0  452.39      .1       0
  664.22     .12       0  784.56      .1       0  804.56     .12       0
  914.56      .1       0  949.95     .12       0
#XS Ineff= 2 , 0
          231.62 2867.36  592.89         2877.07
Permanent Ineff=
       F       F
Bank Sta=405.5,415.5
XS Rating Curve= 0 ,0
Exp/Cntr(USF)=0,0
Exp/Cntr=0.3,0.1

Type RM Length L Ch R = 1 ,200     ,,,
XS GIS Cut Line= 6
2359825.61927659667695.7722357492360130.64021895667926.146446868
2360315.04693383667932.1211940612360351.62448464667922.846278464
2360497.39779765667926.8962896812360638.99325211667922.855510896
#Sta/Elev= 30
       0 2864.26    62.8 2863.62    95.3  2861.4   115.2 2862.41   142.8 2860.82
     217 2862.12   287.7 2860.76   307.6 2861.77   354.1    2860   383.8 2860.88
   411.8 2858.72   431.8 2859.84   447.8 2858.46   500.6 2859.64   527.9 2858.34
   551.9 2859.44   567.9 2858.78   575.82857.079   583.3 2856.74   589.52857.068
     609 2857.88     654 2856.95   749.1 2860.31   757.1 2861.65   773.1 2868.54
   785.1 2871.31   805.1 2873.96   821.1 2873.57   861.1 2877.77     892 2882.45
#Mann= 8 ,-1,0
       0     .12       0      90      .1       0  542.24     .08       0
   575.8    .045       0   589.5     .08       0  734.48      .1       0
  780.31     .08       0  840.31      .1       0
#XS Ineff= 2 , 0
          499.09 2864.84  679.42         2865.72
Permanent Ineff=
       F       F
Bank Sta=575.8,589.5
XS Rating Curve= 0 ,0
Exp/Cntr(USF)=0,0
Exp/Cntr=0.3,0.1
LCMann Table=0

Chan Stop Cuts=-1
Use User Specified Reach Order=0
Composite Channel Slope=5